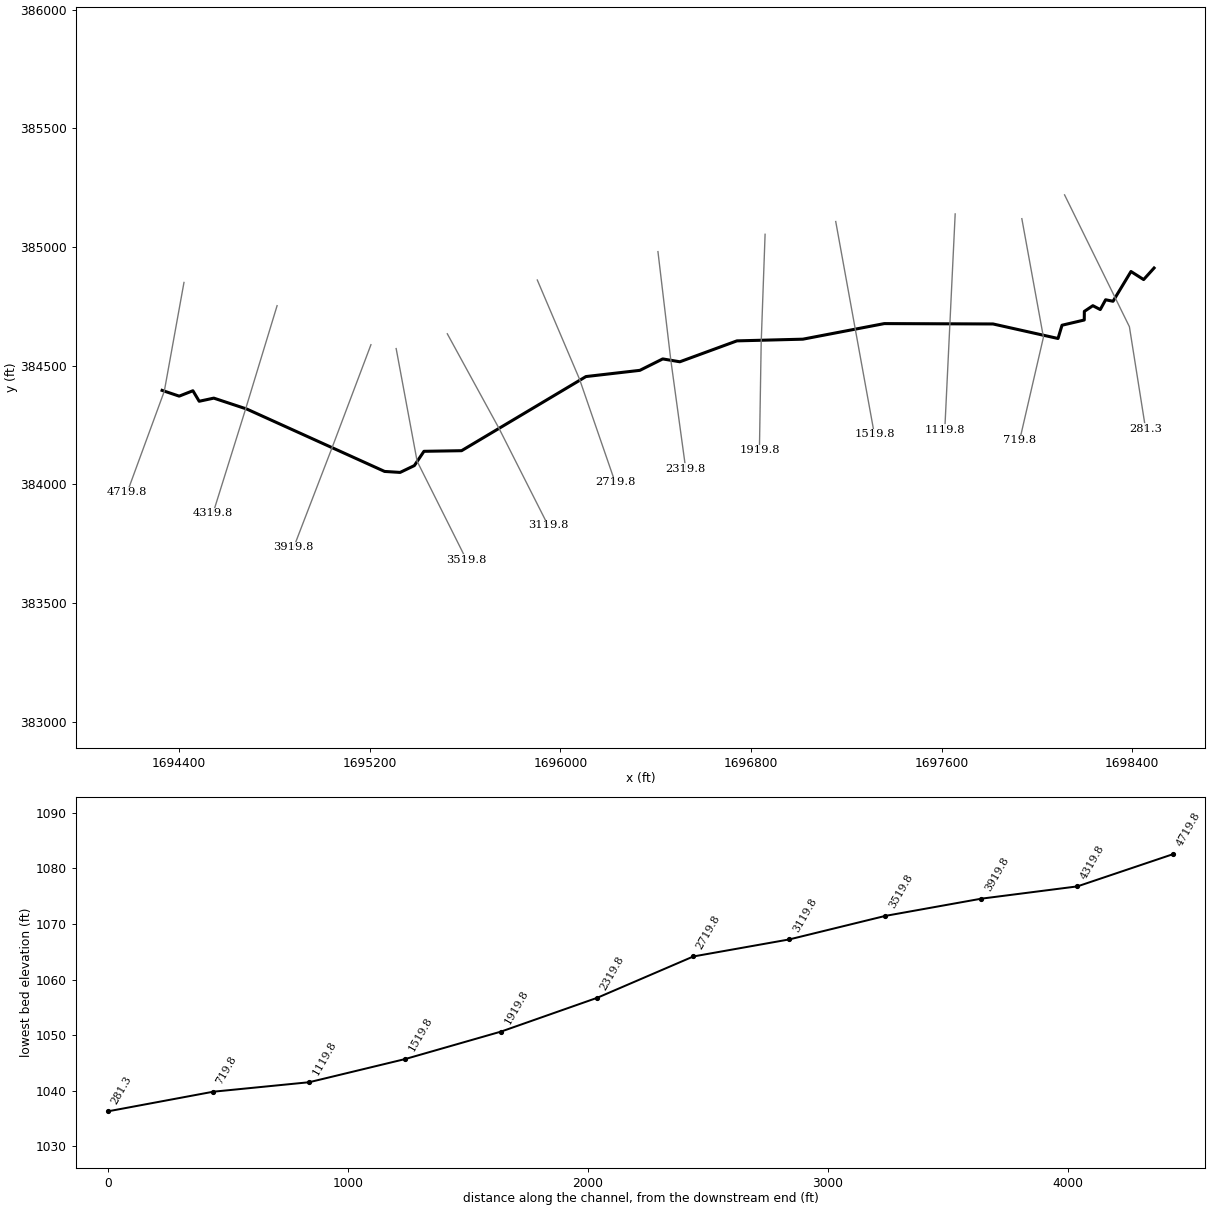
--- EvnsRn.prj (project) ---

Proj Title=EvnsRn
Current Plan=p01
Default Exp/Contr=0,0
English Units
Geom File=g01
Flow File=f01
Plan File=p01
BEGIN DESCRIPTION:
END DESCRIPTION:
DSS Export Rating Curves= 0
DSS Export Rating Curve Sorted= 0
DSS Export Volume Flow Curves= 0
DXF OffsetX= 0
DXF OffsetY= 0
DXF ScaleX= 0
DXF ScaleY= 0

--- EvnsRn.p01 (plan) ---

Plan Title=Floodplain
Program Version=4.00
Geom File=g01
Flow File=f01
K Sum by GR=0
Std Step Tol=0.01
Critical Tol=0.01
Num of Std Step Trials=20
Max Error Tol=0.3
Flow Tol Ratio=0.001
Split Flow NTrial=30
Split Flow Tol=0.02
Split Flow Ratio=0.02
Log Output Level=0
Friction Slope Method=1
Unsteady Friction Slope Method=2
Unsteady Bridges Friction Slope Method=1
Global Log Level=0
CheckData=False
Run HTab=0
Run UNet=0
Run PostProcess=0
UNET Theta=0
UNET Theta Warmup=0
UNET ZTol=0
UNET ZSATol=0
UNET MxIter=0
UNET MaxInSteps=0
UNET DtIC=0
UNET DtMin=0
UNET MaxCRTS=0
UNET WFStab=0
UNET SFStab=0
UNET WFX=0
UNET SFX=0
UNET DSS MLevel=0
UNET DZMax Abort=0
UNET Convert EG Bridges=0
UNET Use Existing IB Tables=0
UNET Froude Limit=0
UNET Froude Power=0
Write IC File=0
Echo Input=False
Echo Output=False
Write Detailed=0

--- EvnsRn.f01 (steady flow) ---

Flow Title=NFF Regression Equation
Program Version=4.00
Number of Profiles=1
Profile Names=P100yr
River Rch & RM=EvnsRn,Main      ,4719.8
618.1768
River Rch & RM=EvnsRn,Main      ,3919.8
622.9331
River Rch & RM=EvnsRn,Main      ,3519.8
687.1114
River Rch & RM=EvnsRn,Main      ,2719.8
700.3337
River Rch & RM=EvnsRn,Main      ,281.3
776.3647
Boundary for River Rch & Prof#=EvnsRn,Main      ,1
Up Type=0
Dn Type=3
Dn Slope=0.008681

--- EvnsRn.g01 (geometry) ---

Geom Title=USGS 3m DEM
Program Version=4.00

River Reach=EvnsRn     ,Main
Reach XY= 30
     1694328.838      384395.716     1694400.617      384371.430
     1694458.157      384394.134     1694484.575      384349.821
     1694545.840      384363.020     1694684.182      384317.070
     1695262.556      384054.174     1695327.559      384050.054
     1695387.385      384078.841     1695427.695      384138.982
     1695585.471      384141.556     1696107.361      384453.896
     1696333.601      384480.102     1696429.513      384528.228
     1696501.330      384516.160     1696740.761      384604.269
     1697017.423      384611.378     1697359.189      384677.025
     1697815.388      384675.504     1698088.199      384614.274
     1698104.915      384670.152     1698198.227      384692.177
     1698198.615      384728.506     1698234.324      384752.489
     1698265.396      384736.159     1698287.865      384777.442
     1698318.997      384771.126     1698394.265      384896.480
     1698447.414      384862.512     1698491.187      384911.262

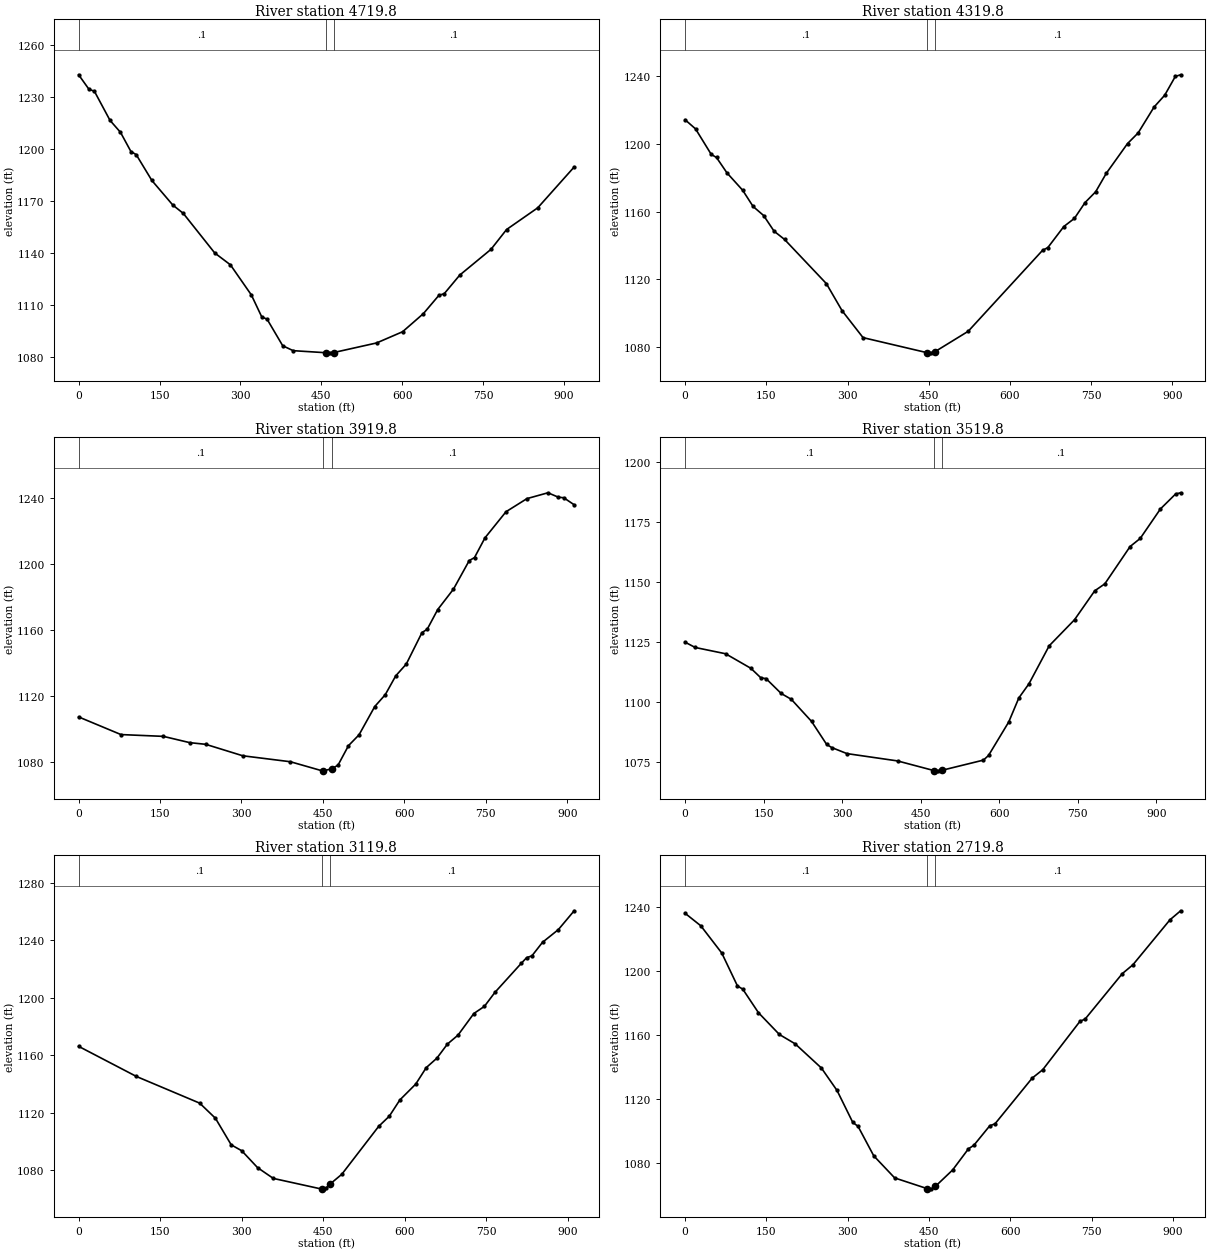
Type RM Length L Ch R = 1 ,4719.8,398.016,400,380.412
XS GIS Cut Line= 3
     1694420.715      384850.390     1694338.149      384392.070
     1694182.724      383966.596
#Sta/Elev= 30
       0 1242.98    19.4 1234.51    29.1 1233.55    58.2 1216.67    77.6 1209.79
    97.0 1198.68   106.7 1196.95   135.8 1182.01   174.6 1167.84   194.0 1163.04
   252.3 1140.21   281.4 1133.36   320.2 1116.00   339.6 1103.26   349.3 1102.05
   378.4 1086.67   397.8 1083.85   458.2 1082.67   465.7 1082.60   473.2 1082.79
   552.4 1088.30   600.6 1094.77   639.2 1105.23   668.1 1115.84   677.7 1116.68
   706.6 1127.45   764.5 1142.30   793.4 1153.73   851.2 1166.26   918.7 1189.79
#Mann= 3 , 0 , 0
       0     0.1       0   458.2   0.045       0   473.2     0.1       0
Bank Sta=   458.2,   473.2
Exp/Cntr=0.3,0.1

Type RM Length L Ch R = 1 ,4319.8,401.519,400,398.503
XS GIS Cut Line= 3
     1694811.396      384752.448     1694679.552      384317.817
     1694542.501      383877.750
#Sta/Elev= 30
       0 1214.03    19.3 1208.66    48.3 1193.63    58.0 1191.81    77.3 1182.76
   106.3 1172.53   125.6 1162.96   145.0 1157.65   164.3 1148.42   183.6 1143.57
   260.9 1117.54   289.9 1101.59   328.6 1085.74   446.7 1076.88   454.2 1076.78
   461.7 1077.51   522.8 1089.47   660.1 1137.14   669.9 1138.78   699.4 1151.16
   719.0 1155.97   738.6 1165.28   758.2 1171.63   777.8 1182.49   817.0 1200.00
   836.6 1206.27   866.1 1221.55   885.7 1228.49   905.3 1239.56   915.1 1240.52
#Mann= 3 , 0 , 0
       0     0.1       0   446.7   0.045       0   461.7     0.1       0
Bank Sta=   446.7,   461.7
Exp/Cntr=0.3,0.1

Type RM Length L Ch R = 1 ,3919.8,399.02,400,417.401
XS GIS Cut Line= 3
     1695205.206      384588.098     1695043.900      384158.962
     1694881.244      383734.681
#Sta/Elev= 30
       0 1107.30    78.0 1096.59   156.1 1095.50   204.8 1091.68   234.1 1090.67
   302.4 1083.71   390.2 1080.09   448.7 1074.57     451 1074.61     466 1075.77
   477.8 1078.03   497.1 1089.87   516.5 1096.43   545.5 1113.63   564.8 1120.79
   584.1 1132.23   603.5 1139.38   632.5 1158.52   642.1 1160.54   661.5 1172.52
   690.5 1184.91   719.5 1202.22   729.2 1204.05   748.5 1216.03   787.2 1231.87
   825.8 1239.84   864.5 1243.39   883.8 1240.69   893.5 1240.38   912.8 1236.11
#Mann= 3 , 0 , 0
       0     0.1       0     451   0.045       0     466     0.1       0
Bank Sta=     451,     466
Exp/Cntr=0.3,0.1

Type RM Length L Ch R = 1 ,3519.8,381.764,400,401.241
XS GIS Cut Line= 3
     1695311.000      384571.789     1695399.029      384096.953
     1695605.899      383682.164
#Sta/Elev= 30
       0 1125.04    19.3 1122.84    77.3 1120.23   125.6 1114.17   144.9 1110.16
   154.5 1109.90   183.5 1103.69   202.8 1101.26   241.5 1092.06   270.4 1082.45
   280.1 1081.16   309.1 1078.65   405.7 1075.60   475.4 1071.57   482.9 1071.47
   490.4 1071.69   569.8 1075.94   579.5 1077.87   618.1 1091.82   637.4 1101.83
   656.7 1107.71   695.4 1123.55   743.7 1134.38   782.3 1146.43   801.6 1149.34
   849.9 1164.88   869.2 1168.25   907.8 1180.53   936.8 1186.76   946.4 1187.26
#Mann= 3 , 0 , 0
       0     0.1       0   475.4   0.045       0   490.4     0.1       0
Bank Sta=   475.4,   490.4
Exp/Cntr=0.3,0.1

Type RM Length L Ch R = 1 ,3119.8,402.096,400,397.051
XS GIS Cut Line= 3
     1695525.673      384634.032     1695743.089      384234.591
     1695948.450      383826.827
#Sta/Elev= 30
       0 1166.29   106.4 1145.33   222.6 1126.81   251.6 1116.29   280.6 1097.82
   300.0 1093.71   329.0 1082.00   358.0 1074.49   445.1 1067.24   447.3 1067.35
   454.8 1067.71   462.3 1070.53   483.9 1077.33   551.9 1110.71   571.3 1117.72
   590.8 1129.06   619.9 1140.04   639.3 1151.51   658.8 1158.05   678.2 1167.87
   697.6 1174.05   726.8 1189.11   746.2 1194.07   765.6 1203.81   814.2 1224.07
   823.9 1227.93   833.6 1229.20   853.1 1238.61   882.2 1247.43   911.3 1260.52
#Mann= 3 , 0 , 0
       0     0.1       0   447.3   0.045       0   462.3     0.1       0
Bank Sta=   447.3,   462.3
Exp/Cntr=0.3,0.1

Type RM Length L Ch R = 1 ,2719.8,405.591,400,396.498
XS GIS Cut Line= 3
     1695903.240      384860.683     1696080.548      384442.526
     1696229.994      384007.942
#Sta/Elev= 30
       0 1236.20    29.0 1228.38    67.6 1211.40    96.6 1190.81   106.3 1188.86
   135.3 1174.13   173.9 1160.53   202.9 1154.72   251.3 1139.62   280.2 1125.58
   309.2 1105.65   318.9 1103.20   347.9 1084.77   386.5 1070.98   446.7 1064.27
   454.2 1064.17   461.7 1065.77   493.3 1075.93   522.6 1089.20   532.4 1091.33
   561.8 1103.53   571.5 1104.77   640.0 1133.29   659.5 1138.54   728.0 1168.68
   737.8 1170.22   806.2 1198.52   825.8 1204.06   894.2 1232.16   913.8 1237.77
#Mann= 3 , 0 , 0
       0     0.1       0   446.7   0.045       0   461.7     0.1       0
Bank Sta=   446.7,   461.7
Exp/Cntr=0.3,0.1

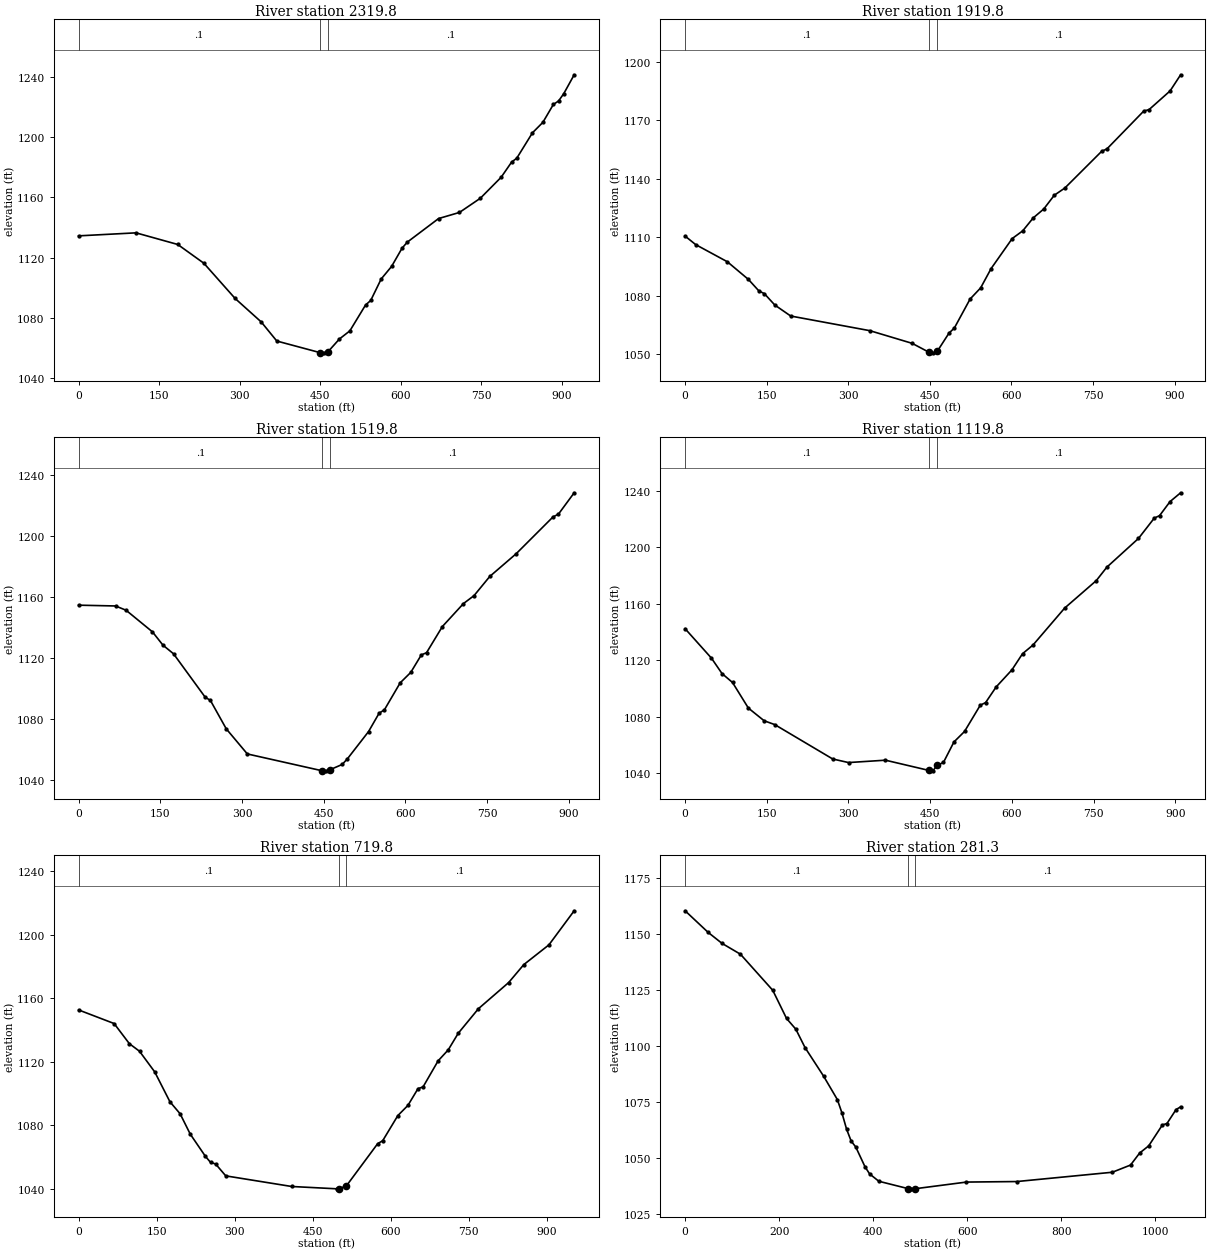
Type RM Length L Ch R = 1 ,2319.8,403.736,400,396.185
XS GIS Cut Line= 3
     1696409.472      384980.274     1696463.050      384526.609
     1696526.133      384064.271
#Sta/Elev= 30
       0 1134.48   106.9 1136.48   184.7 1128.75   233.3 1116.30   291.6 1092.87
   340.2 1077.29   369.3 1064.58   449.3 1056.93   456.8 1056.74   464.3 1057.32
   486.0 1065.95   505.4 1071.34   534.6 1088.50   544.3 1091.55   563.8 1105.83
   583.2 1114.18   602.6 1126.24   612.4 1130.30   670.7 1145.97   709.6 1150.04
   748.5 1159.45   787.3 1173.41   806.8 1183.48   816.5 1186.12   845.7 1202.97
   865.1 1209.92   884.6 1221.78   894.3 1224.12   904.0 1228.97   923.4 1241.52
#Mann= 3 , 0 , 0
       0     0.1       0   449.3   0.045       0   464.3     0.1       0
Bank Sta=   449.3,   464.3
Exp/Cntr=0.3,0.1

Type RM Length L Ch R = 1 ,1919.8,395.161,400,404.402
XS GIS Cut Line= 3
     1696859.031      385053.314     1696842.679      384597.340
     1696835.216      384142.598
#Sta/Elev= 30
       0 1110.59    19.4 1106.23    77.7 1097.41   116.5 1088.33   135.9 1082.38
   145.6 1081.09   165.0 1075.19   194.2 1069.56   339.8 1062.04   417.4 1055.55
   448.8 1050.92   456.3 1050.67   463.8 1051.53   485.3 1060.83   495.0 1063.38
   524.0 1078.28   543.4 1084.01   562.7 1093.95   601.4 1109.32   620.8 1113.29
   640.1 1119.93   659.5 1124.51   678.8 1131.56   698.2 1135.25   765.9 1154.10
   775.6 1155.34   843.3 1174.77   853.0 1175.49   891.7 1185.09   911.1 1193.38
#Mann= 3 , 0 , 0
       0     0.1       0   448.8   0.045       0   463.8     0.1       0
Bank Sta=   448.8,   463.8
Exp/Cntr=0.3,0.1

Type RM Length L Ch R = 1 ,1519.8,405.111,400,394.889
XS GIS Cut Line= 3
     1697155.419      385107.047     1697236.431      384659.317
     1697317.443      384211.587
#Sta/Elev= 30
       0 1154.39    67.8 1153.87    87.1 1151.07   135.5 1136.91   154.9 1128.15
   174.3 1122.49   232.3 1094.07   242.0 1091.90   271.1 1073.27   309.8 1056.80
   447.5 1045.74   455.0 1045.72   462.5 1046.59   484.0 1049.91   493.7 1053.67
   532.4 1071.47   551.8 1083.53   561.5 1085.74   590.5 1103.45   609.9 1110.28
   629.3 1121.76   638.9 1123.22   668.0 1140.39   706.7 1155.45   726.1 1160.65
   755.1 1173.26   803.5 1188.14   871.3 1212.34   881.0 1214.05   910.0 1228.12
#Mann= 3 , 0 , 0
       0     0.1       0   447.5   0.045       0   462.5     0.1       0
Bank Sta=   447.5,   462.5
Exp/Cntr=0.3,0.1

Type RM Length L Ch R = 1 ,1119.8,394.345,400,395.997
XS GIS Cut Line= 3
     1697656.640      385139.046     1697634.824      384684.570
     1697613.008      384230.093
#Sta/Elev= 30
       0 1142.32    48.4 1121.44    67.8 1110.51    87.1 1104.18   116.2 1086.04
   145.2 1077.04   164.6 1074.34   271.1 1049.95   300.1 1047.42   367.9 1049.10
   447.5 1041.87   455.0 1041.55   462.5 1045.34   474.4 1047.48   493.7 1062.02
   513.1 1069.44   542.1 1088.10   551.8 1089.92   571.2 1101.02   600.2 1113.14
   619.6 1124.56   638.9 1130.75   697.0 1156.93   755.1 1176.41   774.5 1185.94
   832.6 1206.32   861.6 1220.73   871.3 1222.47   890.6 1232.45   910.0 1238.68
#Mann= 3 , 0 , 0
       0     0.1       0   447.5   0.045       0   462.5     0.1       0
Bank Sta=   447.5,   462.5
Exp/Cntr=0.3,0.1

Type RM Length L Ch R = 1 ,719.8,421.598,438.558,438.736
XS GIS Cut Line= 3
     1697936.345      385119.025     1698026.971      384619.769
     1697927.130      384185.344
#Sta/Elev= 30
       0 1152.54    68.3 1143.97    97.6 1131.28   117.1 1126.52   146.4 1113.49
   175.6 1094.71   195.2 1087.13   214.7 1074.32   243.9 1060.30   253.7 1056.52
   263.5 1055.50   283.0 1048.01   409.8 1041.32   497.7 1039.84   499.9 1039.87
   514.9 1041.64   575.2 1068.29   584.9 1070.17   614.0 1085.98   633.4 1092.40
   652.8 1102.96   662.5 1104.03   691.5 1120.48   710.9 1127.36   730.3 1137.89
   769.1 1153.34   827.2 1169.80   856.3 1181.09   904.7 1193.56   953.2 1215.01
#Mann= 3 , 0 , 0
       0     0.1       0   499.9   0.045       0   514.9     0.1       0
Bank Sta=   499.9,   514.9
Exp/Cntr=0.3,0.1

Type RM Length L Ch R = 1 ,281.3,266.99,281.262,258.796
XS GIS Cut Line= 3
     1698115.648      385219.324     1698387.643      384664.000
     1698455.642      384233.341
#Sta/Elev= 30
       0 1160.33    49.1 1150.68    78.5 1145.80   117.8 1140.95   186.5 1124.87
   215.9 1112.29   235.6 1107.52   255.2 1099.31   294.5 1086.64   323.9 1076.15
   333.7 1070.20   343.5 1062.99   353.3 1057.64   363.2 1054.95   382.8 1046.15
   392.6 1042.97   412.2 1039.69   475.2 1036.37   480.9 1036.31   490.2 1036.38
   598.7 1039.33   705.6 1039.56   909.0 1043.71   947.8 1046.92   967.2 1052.28
   986.5 1055.49  1015.6 1064.82  1025.3 1065.45  1044.7 1071.68  1054.4 1072.88
#Mann= 3 , 0 , 0
       0     0.1       0   475.2   0.045       0   490.2     0.1       0
Bank Sta=   475.2,   490.2
Exp/Cntr=0.3,0.1